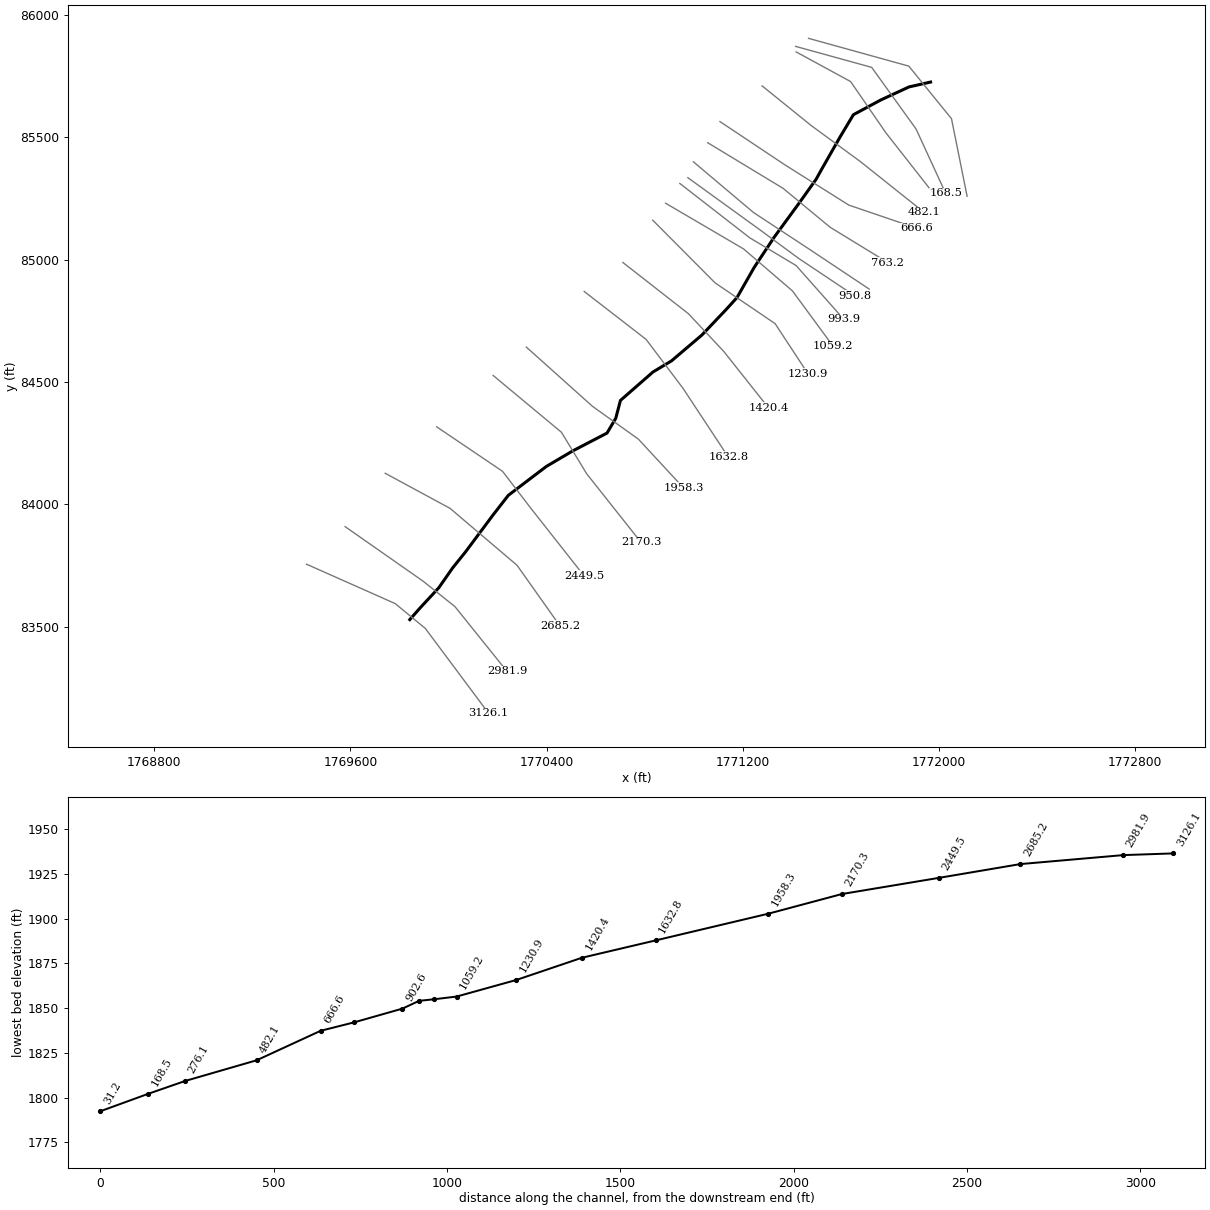
--- Vall Creek Trib 1.prj (project) ---

Proj Title=Vall Creek Trib 1
Current Plan=p01
Default Exp/Contr=0,0
English Units
Geom File=g01
Flow File=f01
Plan File=p01
BEGIN DESCRIPTION:
END DESCRIPTION:
DSS Export Rating Curves= 0
DSS Export Rating Curve Sorted= 0
DSS Export Volume Flow Curves= 0
DXF OffsetX= 0
DXF OffsetY= 0
DXF ScaleX= 0
DXF ScaleY= 0

--- Vall Creek Trib 1.p01 (plan) ---

Plan Title=Floodplain
Program Version=4.00
Geom File=g01
Flow File=f01
K Sum by GR=0
Std Step Tol=0.01
Critical Tol=0.01
Num of Std Step Trials=20
Max Error Tol=0.3
Flow Tol Ratio=0.001
Split Flow NTrial=30
Split Flow Tol=0.02
Split Flow Ratio=0.02
Log Output Level=0
Friction Slope Method=1
Unsteady Friction Slope Method=2
Unsteady Bridges Friction Slope Method=1
Global Log Level=0
CheckData=False
Run HTab=0
Run UNet=0
Run PostProcess=0
UNET Theta=0
UNET Theta Warmup=0
UNET ZTol=0
UNET ZSATol=0
UNET MxIter=0
UNET MaxInSteps=0
UNET DtIC=0
UNET DtMin=0
UNET MaxCRTS=0
UNET WFStab=0
UNET SFStab=0
UNET WFX=0
UNET SFX=0
UNET DSS MLevel=0
UNET DZMax Abort=0
UNET Convert EG Bridges=0
UNET Use Existing IB Tables=0
UNET Froude Limit=0
UNET Froude Power=0
Write IC File=0
Echo Input=False
Echo Output=False
Write Detailed=0

--- Vall Creek Trib 1.f01 (steady flow) ---

Flow Title=NFF Regression Equation
Program Version=4.00
Number of Profiles=1
Profile Names=P100yr
River Rch & RM=Vall Creek Tr...,Main      ,3126.1
595.0831
River Rch & RM=Vall Creek Tr...,Main      ,276.1
653.7380
Boundary for River Rch & Prof#=Vall Creek Tr...,Main      ,1
Up Type=0
Dn Type=3
Dn Slope=0.054888

--- Vall Creek Trib 1.g01 (geometry) ---

Geom Title=USGS 10m DEM
Program Version=4.00

River Reach=Vall Creek Tr...,Main
Reach XY= 27
     1769842.054       83528.406     1769882.749       83574.676
      1769960.48       83658.809     1770017.178       83740.198
     1770069.304       83805.126     1770182.096       83956.704
     1770243.934       84036.407     1770399.216       84154.586
     1770506.402       84217.799     1770646.343       84290.717
     1770682.007       84351.073     1770701.212       84424.231
     1770833.812       84540.371     1770909.714       84586.095
     1771033.169        84691.26     1771133.762        84797.34
     1771176.743       84844.893       1771246.5       84967.653
     1771328.547       85091.804     1771430.055       85230.805
     1771499.555       85328.655     1771523.332       85371.636
     1771598.017        85502.83      1771651.36       85592.026
     1771763.282       85652.283     1771878.151       85705.422
     1771965.944       85725.375

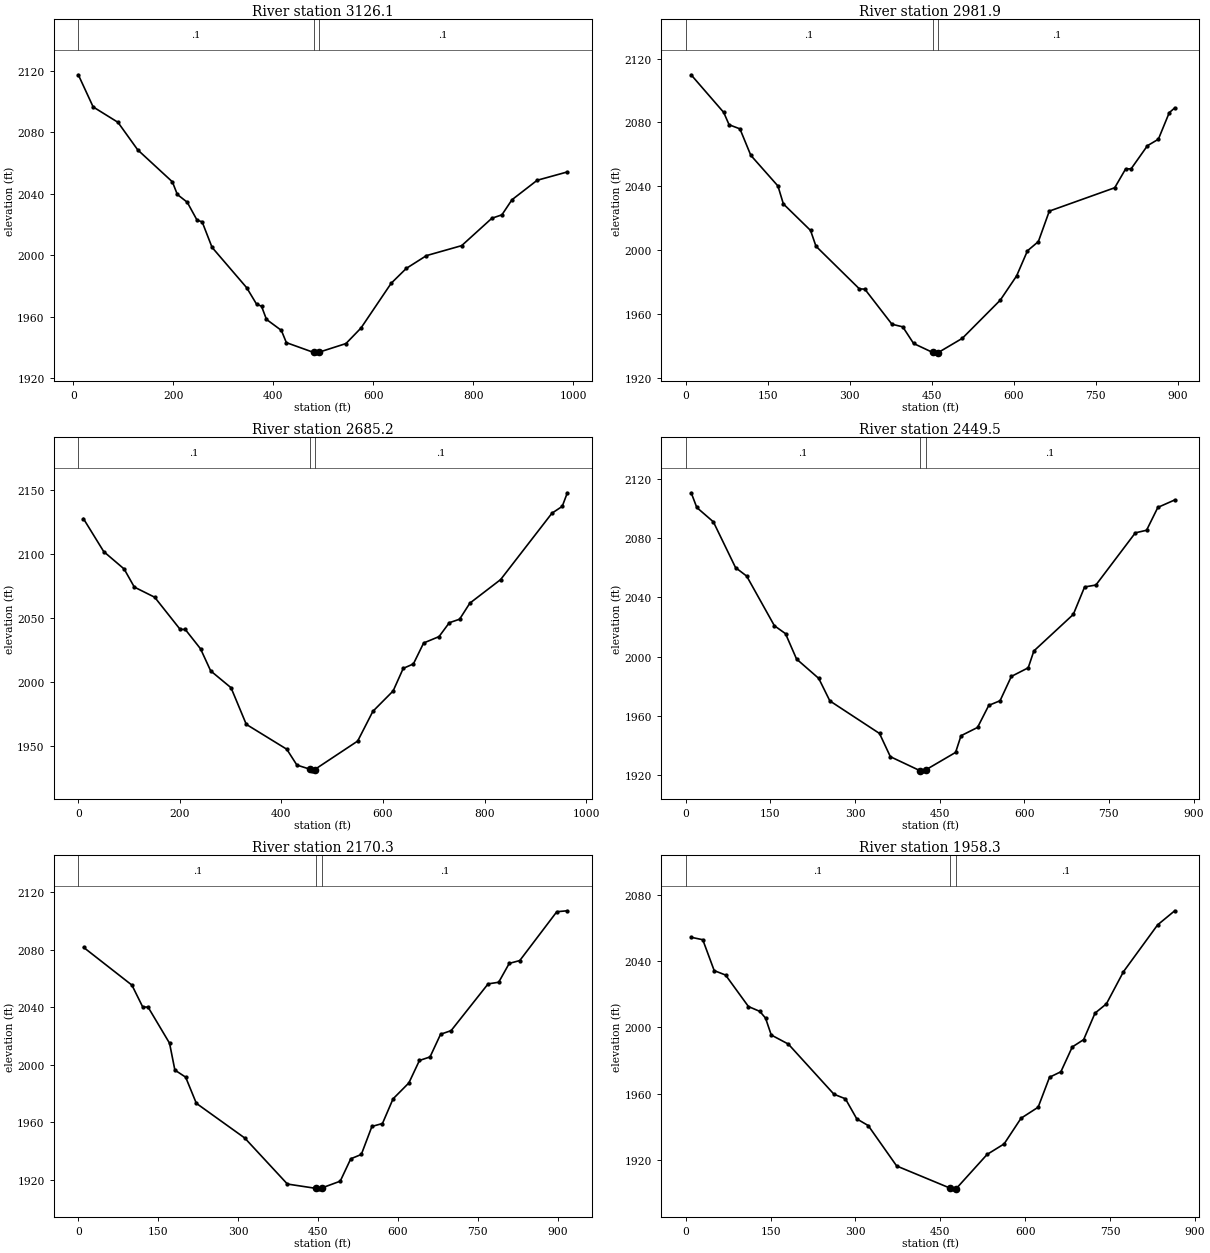
Type RM Length L Ch R = 1 ,3126.1  ,143.9,144.2,144.5
XS GIS Cut Line= 4
     1769420.773       83755.001     1769782.767       83593.868
     1769905.343       83492.526      1770163.78       83145.251
#Sta/Elev= 30
     9.9 2117.22    39.6 2096.32    89.2 2086.32   128.8 2068.39   198.1 2047.62
     208 2039.41   227.8 2034.37   247.6 2022.62   257.6 2021.65   277.4 2005.06
   346.7 1978.81   366.5 1968.11   376.4 1966.76   386.3  1958.2   416.1 1951.05
   426.1 1943.09   480.7 1936.72  485.73 1936.46   490.7  1936.8   545.3 1942.49
   575.4  1952.6   635.8 1981.69     666 1991.35   706.3 1999.66   776.8 2006.15
   837.2 2023.95   857.3 2026.18   877.4 2035.97   927.8 2048.64   988.2 2054.06
#Mann= 3 , 0 , 0
     9.9      .1       0   480.7    .045       0   490.7      .1       0
Bank Sta=480.7,490.7
XS Rating Curve= 0 ,0
Exp/Cntr=0.3,0.1

Type RM Length L Ch R = 1 ,2981.9  ,297.3,296.7,296
XS GIS Cut Line= 4
     1769578.258       83908.449     1769895.247       83686.354
     1770026.485       83581.364     1770238.484        83316.87
#Sta/Elev= 30
     9.9 2109.84    69.5 2086.26    79.4 2078.51    99.2 2075.93   119.1 2059.33
   168.7 2040.11   178.6 2028.88   228.3 2012.24   238.2 2002.37   317.6 1975.61
   327.5 1975.46   377.1 1953.45   396.9 1951.81   416.7 1941.38   451.3  1935.8
   456.3 1935.51   461.3  1935.6   505.7 1944.59   575.1 1968.52     605 1983.72
   624.9  1999.5   644.8 2005.25   664.8 2024.36   784.4 2039.01   804.4 2050.85
   814.3 2050.85   844.2 2065.37   864.2 2069.43   884.1 2086.09   894.1 2089.06
#Mann= 3 , 0 , 0
       0      .1       0   451.3    .045       0   461.3      .1       0
Bank Sta=451.3,461.3
XS Rating Curve= 0 ,0
Exp/Cntr=0.3,0.1

Type RM Length L Ch R = 1 ,2685.2  ,240,235.7,231.4
XS GIS Cut Line= 4
       1769741.8       84126.505     1770006.295       83983.153
     1770279.659       83750.404     1770454.522       83502.621
#Sta/Elev= 30
      10 2127.51    50.1  2101.7    90.3 2088.11   110.3 2074.01   150.4 2066.08
   200.6 2040.94   210.6 2040.94   240.7 2025.81   260.7 2008.56   300.8 1995.39
   330.8 1966.81   410.5 1947.38   430.5    1935   455.4 1931.88   460.4  1930.5
   465.4 1931.47   550.2 1953.77   580.1 1976.97     620 1992.89   639.9 2010.52
   659.9 2013.99   680.1 2030.35   710.4 2035.33   730.6 2046.16   750.9 2048.92
   771.1 2061.45   831.7 2079.87   932.8 2131.71     953 2137.04   963.1 2147.65
#Mann= 3 , 0 , 0
       0      .1       0   455.4    .045       0   465.4      .1       0
Bank Sta=455.4,465.4
XS Rating Curve= 0 ,0
Exp/Cntr=0.3,0.1

Type RM Length L Ch R = 1 ,2449.5  ,281.3,279.2,277
XS GIS Cut Line= 4
      1769951.78       84316.295     1770220.313       84134.581
      1770331.36        83989.21     1770553.455       83706.544
#Sta/Elev= 30
     9.8 2110.81    19.7 2100.86    49.1 2091.14    88.4 2060.19   108.1 2054.47
   157.2  2020.9   176.9 2015.55   196.5 1998.37   235.8 1985.28   255.5 1970.06
   343.5 1948.04   362.7 1932.34   415.5 1922.82   420.5 1922.77   425.5 1923.44
   478.3 1935.23   487.9 1946.51   517.2 1952.12   537.1 1967.04   557.1 1970.18
   577.1 1986.62     607 1992.45     617 2003.83   686.9 2028.56   706.9 2047.12
   726.9 2048.42   796.8 2083.72   816.7 2085.46   836.7 2100.92   866.6 2105.96
#Mann= 3 , 0 , 0
       0      .1       0   415.5    .045       0   425.5      .1       0
Bank Sta=415.5,425.5
XS Rating Curve= 0 ,0
Exp/Cntr=0.3,0.1

Type RM Length L Ch R = 1 ,2170.3  ,203.7,212,220.4
XS GIS Cut Line= 4
     1770181.951       84526.275     1770460.579       84294.085
      1770563.55       84124.486     1770784.928       83844.425
#Sta/Elev= 30
    10.1 2081.75   100.7 2055.51   120.9 2040.34     131 2040.21   171.3  2015.1
   181.3  1996.4   201.5 1991.49   221.6 1973.27   312.3 1949.18   392.5  1917.1
     447 1914.04     452 1913.76     457 1914.36   491.7 1919.09   511.5 1934.67
   531.3 1937.69   551.2 1957.18     571 1959.23   590.9 1976.39   620.6 1987.47
   640.4 2003.09   660.3 2005.56   680.1 2021.33   699.9 2023.87   769.3 2056.39
   789.2 2057.53     809 2070.65   828.8 2072.63   898.3 2106.62   918.1 2107.27
#Mann= 3 , 0 , 0
       0      .1       0     447    .045       0     457      .1       0
Bank Sta=447,457
XS Rating Curve= 0 ,0
Exp/Cntr=0.3,0.1

Type RM Length L Ch R = 1 ,1958.3  ,331.9,325.5,319.1
XS GIS Cut Line= 4
     1770317.479       84642.117     1770587.526       84399.832
     1770774.287       84266.071     1770958.524       84066.691
#Sta/Elev= 30
    10.1 2054.22    30.2 2052.78    50.4 2034.18    70.5 2031.51   110.9 2012.55
     131 2009.63   141.1 2005.58   151.2 1995.41   181.4 1989.94     262 1959.74
   282.2    1957   302.3 1944.91   322.5 1940.88   372.8 1916.54   467.7 1903.12
   472.7 1902.78   477.7 1902.81   532.6 1923.51   562.6 1929.83   592.5 1945.29
   622.7 1951.92   642.8 1969.97   662.9 1973.29     683 1988.21   703.1 1992.63
   723.2 2008.58   743.3 2014.16   773.5 2033.55   833.8 2061.73     864 2070.21
#Mann= 3 , 0 , 0
       0      .1       0   467.7    .045       0   477.7      .1       0
Bank Sta=467.7,477.7
XS Rating Curve= 0 ,0
Exp/Cntr=0.3,0.1

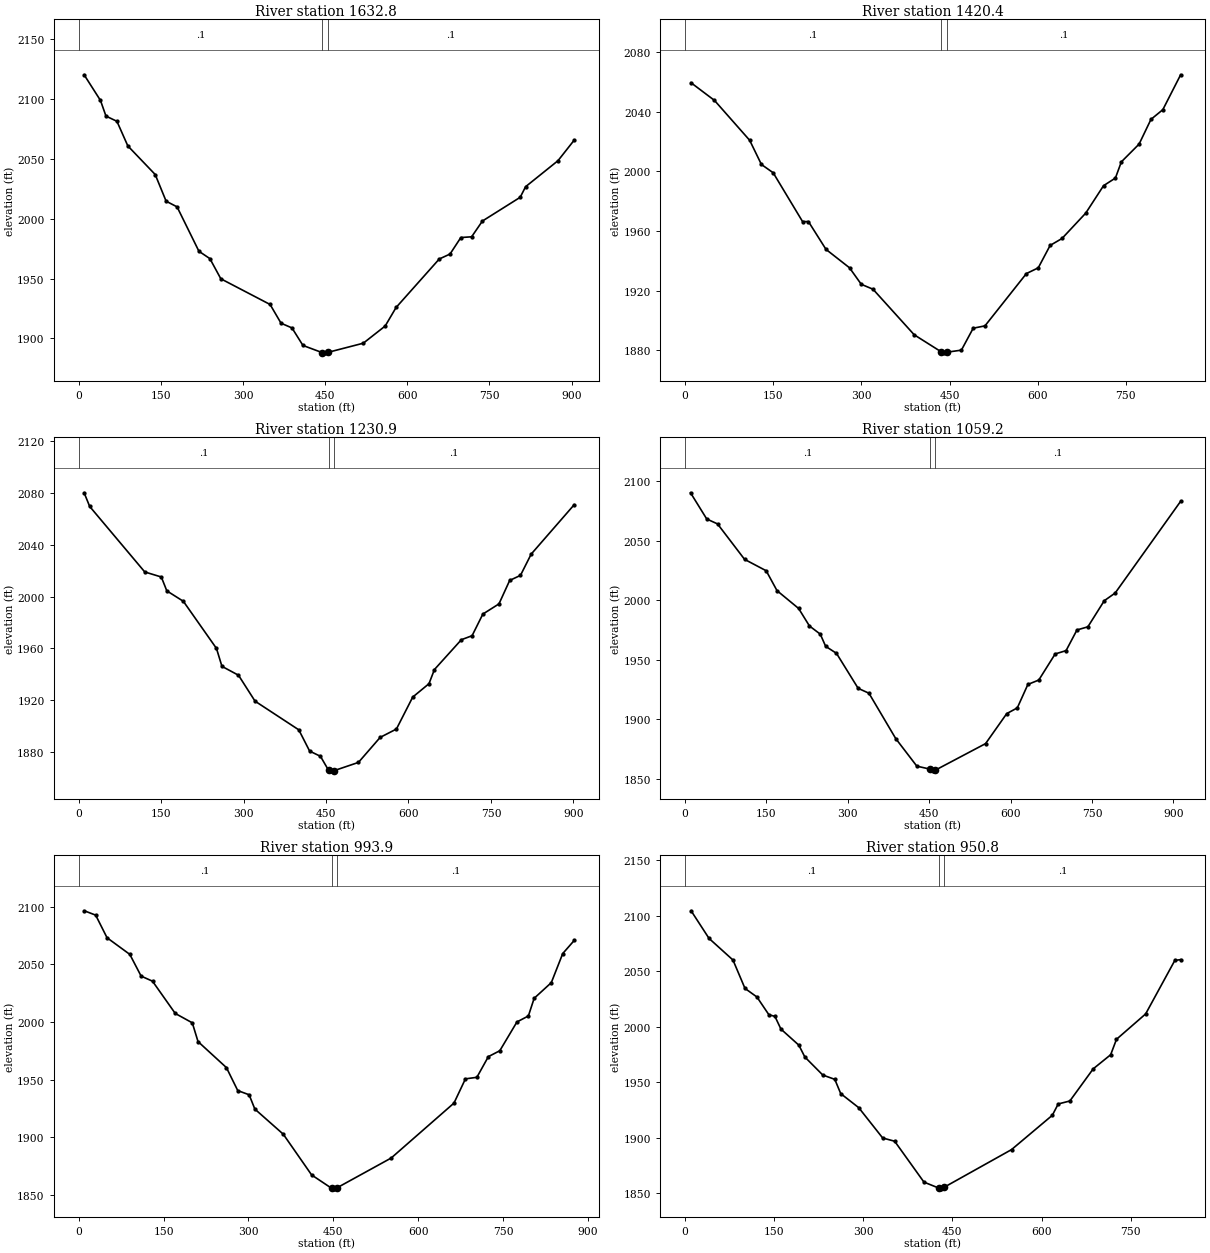
Type RM Length L Ch R = 1 ,1632.8  ,210.3,212.4,214.5
XS GIS Cut Line= 4
     1770553.455       84869.512     1770805.835       84673.665
     1770956.294       84473.834       1771140.4       84193.922
#Sta/Elev= 30
      10 2120.41    39.9 2098.93    49.9 2085.86    69.9 2081.49    89.8 2060.91
   139.8 2036.97   159.7 2014.68   179.7 2009.92   219.6 1972.79   239.6 1966.63
   259.6 1949.76   349.5 1928.28   369.5 1912.61   389.5 1908.66   409.5 1894.01
   444.5 1888.04   449.5 1887.83   454.5 1888.16   519.6 1895.88   559.6 1910.26
   579.5 1925.76   658.3 1966.31     678 1970.48   697.7 1984.27   717.4 1984.89
   737.1 1998.07   806.1 2017.94   815.9 2026.78   875.1 2048.57   904.6 2065.71
#Mann= 3 , 0 , 0
       0      .1       0   444.5    .045       0   454.5      .1       0
Bank Sta=444.5,454.5
XS Rating Curve= 0 ,0
Exp/Cntr=0.3,0.1

Type RM Length L Ch R = 1 ,1420.4  ,185.1,189.5,194
XS GIS Cut Line= 4
     1770711.192       84987.878     1770978.715       84778.403
     1771122.572       84624.451     1771304.285       84394.785
#Sta/Elev= 30
      10 2059.57      50 2047.68   109.9 2020.89   129.9 2004.65   149.9 1999.09
   199.9 1966.31   209.9 1966.31   239.8 1947.63   279.8 1935.27   299.8 1924.19
   319.8 1920.87   389.9 1890.27   435.1 1879.02   440.1 1878.15   445.1 1878.56
   470.2 1879.96   490.3  1894.7   510.3 1896.26   580.8 1931.38     601 1935.24
   621.2 1950.29   641.4 1954.95   681.8 1971.99   712.1 1990.41   732.3 1995.54
   742.4 2006.41   772.6 2018.35   792.8 2034.95     813 2041.47   843.3  2064.9
#Mann= 3 , 0 , 0
       0      .1       0   435.1    .045       0   445.1      .1       0
Bank Sta=435.1,445.1
XS Rating Curve= 0 ,0
Exp/Cntr=0.3,0.1

Type RM Length L Ch R = 1 ,1230.9  ,174,171.7,169.4
XS GIS Cut Line= 4
     1770832.898       85160.752     1771087.238       84904.593
     1771332.047       84738.022     1771465.808       84533.594
#Sta/Elev= 30
      10 2079.94    20.1 2069.41   120.3 2018.94   150.4 2015.06   160.4 2004.39
   190.5 1996.33   250.7 1960.05   260.7 1946.22   290.8 1939.37   320.9  1919.4
   400.5  1897.3   420.2 1880.94   439.9 1876.91   454.7 1866.09   459.7 1865.72
   464.7 1865.86     509 1872.22   548.5 1891.49   578.1 1897.93   607.7 1922.53
   637.3 1932.85   647.2 1943.76   696.2 1966.74   715.7 1969.82   735.3 1986.49
   764.6 1994.34   784.1 2012.41   803.7  2016.3   823.2 2032.68   901.4 2070.72
#Mann= 3 , 0 , 0
       0      .1       0   454.7    .045       0   464.7      .1       0
Bank Sta=454.7,464.7
XS Rating Curve= 0 ,0
Exp/Cntr=0.3,0.1

Type RM Length L Ch R = 1 ,1059.2  ,61.9,65.3,68.7
XS GIS Cut Line= 4
     1770885.334       85230.163     1771203.333       85043.402
     1771402.713       84871.783     1771569.284       84644.641
#Sta/Elev= 30
      10 2090.38    39.9 2068.33    59.8 2064.19   109.6 2034.39   149.5 2024.78
   169.4 2008.08   209.3 1993.06   229.2 1978.35   249.2 1971.46   259.1 1961.23
   279.1 1955.31     319 1925.89   338.9 1921.77   388.3 1883.62   427.2 1860.42
   451.5 1857.92   456.5 1856.48   461.5  1857.1   553.9 1879.38   592.9 1904.61
   612.4 1909.43   631.9 1929.16     652 1932.86   682.2 1954.81   702.3  1957.6
   722.4 1974.99   742.5 1977.63   772.7 1999.57   792.8 2006.05   913.5  2083.2
#Mann= 3 , 0 , 0
       0      .1       0   451.5    .045       0   461.5      .1       0
Bank Sta=451.5,461.5
XS Rating Curve= 0 ,0
Exp/Cntr=0.3,0.1

Type RM Length L Ch R = 1 ,993.9   ,45,43.1,41.1
XS GIS Cut Line= 4
     1770943.382       85310.924     1771228.571        85088.83
     1771417.856       84975.259     1771612.189       84755.688
#Sta/Elev= 30
      10  2096.7    30.1 2092.91    50.2 2073.24    90.4 2058.79   110.4  2039.9
   130.5 2035.48   170.7 2007.43   200.8 1999.28   210.9 1982.98   261.1 1960.34
   281.1 1940.37   301.2 1936.72   311.3 1924.29   361.5 1902.45   411.6 1867.03
   446.8 1855.46   451.8 1854.94   456.8 1855.93   552.1 1881.72   663.1 1929.51
   683.3 1950.56   703.5  1951.9   723.8 1969.88     744 1975.01   774.3 2000.04
   794.5 2005.24   804.7  2020.6     835 2034.21   855.2  2059.5   875.4 2070.86
#Mann= 3 , 0 , 0
       0      .1       0   446.8    .045       0   456.8      .1       0
Bank Sta=446.8,456.8
XS Rating Curve= 0 ,0
Exp/Cntr=0.3,0.1

Type RM Length L Ch R = 1 ,950.8   ,47.2,48.3,49.3
XS GIS Cut Line= 4
       1770976.2       85334.493     1771269.932       85121.494
     1771427.962       85004.689      1771656.42       84851.811
#Sta/Elev= 30
    10.1 2104.34    40.3 2079.47    80.6 2060.01   100.8 2034.48   120.9 2026.75
   141.1 2010.74   151.2 2009.32   161.3 1997.89   191.5 1983.38   201.6 1972.73
   231.8  1956.5     252 1952.62     262 1939.78   292.3 1927.13   332.6 1899.85
   352.8 1896.92   402.1 1860.13   426.6 1854.87   431.6 1854.08   436.6 1855.66
   549.5 1889.38   618.2 1920.28   628.1 1930.47   647.7 1933.15     687 1962.07
   716.4 1974.78   726.2 1988.67   775.3 2011.52   824.4 2059.64   834.2 2060.39
#Mann= 3 , 0 , 0
       0      .1       0   426.6    .045       0   436.6      .1       0
Bank Sta=426.6,436.6
XS Rating Curve= 0 ,0
Exp/Cntr=0.3,0.1

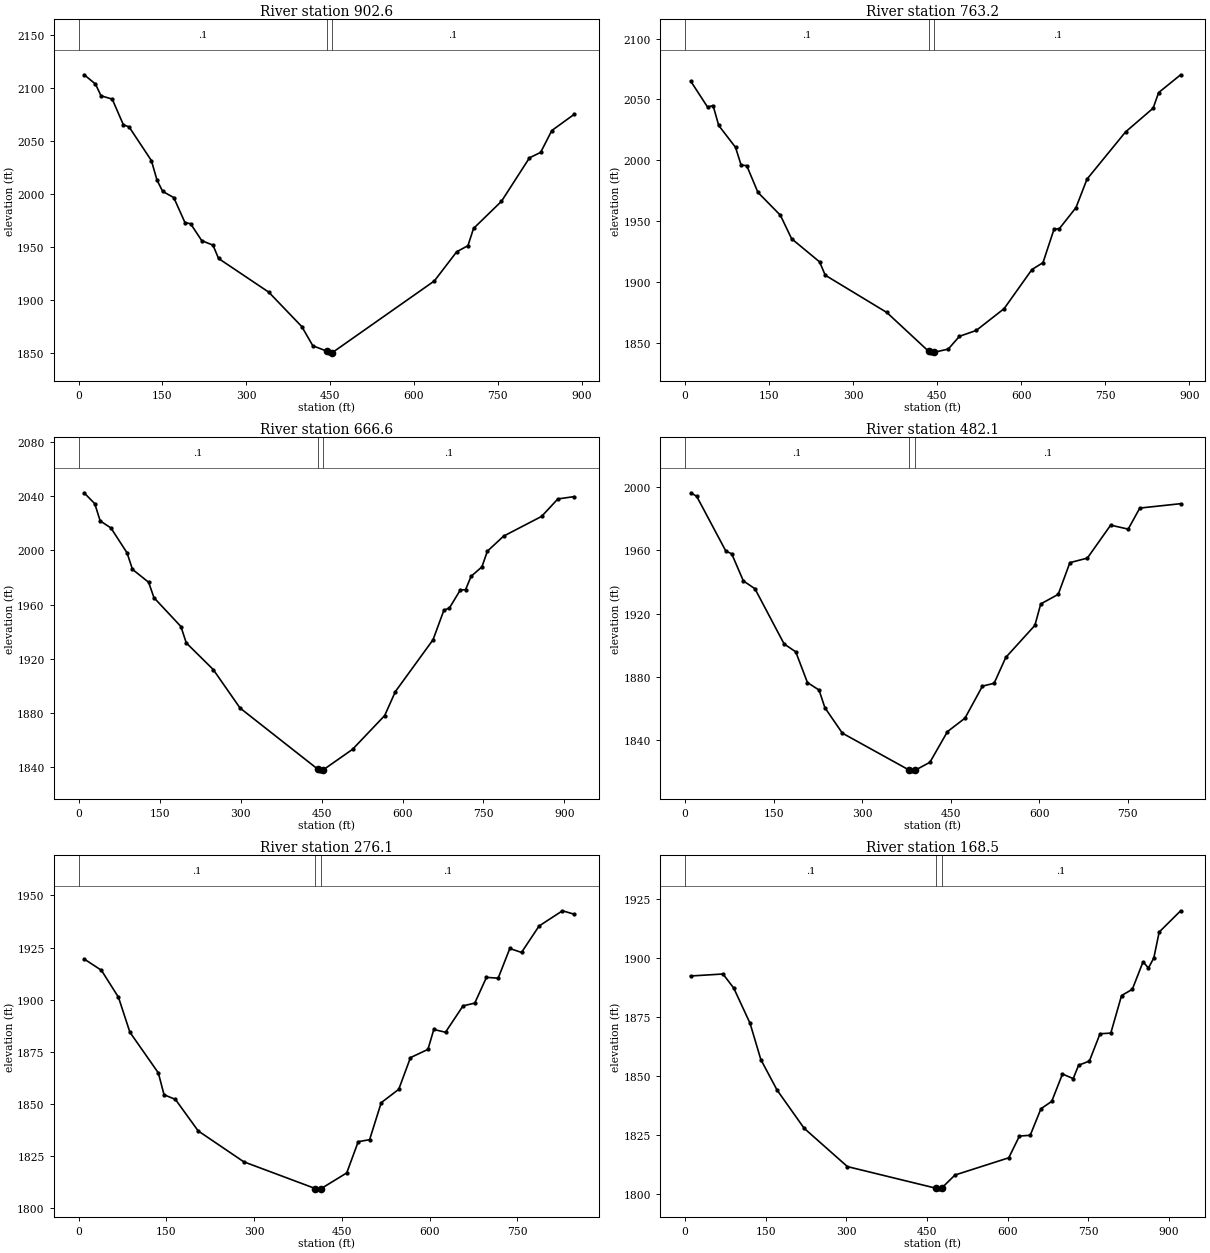
Type RM Length L Ch R = 1 ,902.6   ,141.6,139.4,137.2
XS GIS Cut Line= 4
     1770998.905       85399.257     1771243.714       85192.306
     1771465.808       85045.925     1771715.665       84879.355
#Sta/Elev= 30
      10 2112.38    30.1 2103.65    40.1 2092.51    60.1 2089.42    80.1  2065.1
    90.2  2063.2   130.2 2031.34   140.2 2012.99   150.3 2002.27   170.3 1996.36
   190.3 1972.75   200.4 1971.66   220.4 1955.65   240.4 1951.47   250.4 1938.86
   340.3 1907.01   399.4 1874.49   419.1 1856.41   443.6 1851.42   448.6 1849.72
   453.6 1849.79   636.6 1917.64   676.6  1945.2   696.7 1950.94   706.7 1967.22
   756.7 1992.86   806.8 2033.93   826.8 2039.08   846.8 2059.72   886.8    2075
#Mann= 3 , 0 , 0
       0      .1       0   443.6    .045       0   453.6      .1       0
Bank Sta=443.6,453.6
XS Rating Curve= 0 ,0
Exp/Cntr=0.3,0.1

Type RM Length L Ch R = 1 ,763.2   ,94.1,96.6,99.2
XS GIS Cut Line= 4
     1771056.953       85477.495     1771364.856       85290.734
     1771556.665       85131.735     1771791.379       84987.878
#Sta/Elev= 30
      10 2065.05      40 2043.81      50 2044.95      60 2028.64      90 2010.71
     100 1996.11     110 1995.68     130 1973.72   170.1 1954.94   190.1 1935.69
   240.1 1916.67   250.1 1905.77   360.1 1875.15   434.8 1843.24   439.8 1842.04
   444.8 1842.52   469.7 1845.13   489.7 1855.61   519.6  1860.4   569.4  1878.3
   619.1 1910.42   638.8 1916.04   658.4 1943.35   668.2 1944.06   697.7 1961.22
   717.4 1984.62   786.2 2023.36   835.4 2042.82   845.2 2055.61   884.5 2070.24
#Mann= 3 , 0 , 0
       0      .1       0   434.8    .045       0   444.8      .1       0
Bank Sta=434.8,444.8
XS Rating Curve= 0 ,0
Exp/Cntr=0.3,0.1

Type RM Length L Ch R = 1 ,666.6   ,185.9,184.5,183
XS GIS Cut Line= 4
     1771107.077       85563.839     1771372.428       85386.638
     1771632.379       85222.591     1771908.273       85128.375
#Sta/Elev= 30
      10 2042.47    29.9 2034.42    39.9 2021.72    59.8 2016.53    89.7 1998.13
    99.7 1985.99   129.6 1976.47   139.6 1965.04   189.5 1943.79   199.4 1931.71
   249.3 1912.08   299.1 1883.62     443 1838.56     448 1837.32     453 1838.02
   507.5 1853.21     567 1878.13   586.8 1895.81   656.6 1934.07   676.7 1955.88
   686.8 1957.39   706.9 1970.65   716.9 1971.02     727 1980.83   747.1 1987.79
   757.2 1999.38   787.3 2010.49   857.7 2025.05   887.8 2037.93     918 2039.64
#Mann= 3 , 0 , 0
       0      .1       0     443    .045       0     453      .1       0
Bank Sta=443,453
XS Rating Curve= 0 ,0
Exp/Cntr=0.3,0.1

Type RM Length L Ch R = 1 ,482.1   ,213,206,199
XS GIS Cut Line= 4
     1771279.047       85709.685     1771478.427       85548.162
     1771677.808       85401.781     1771940.283       85192.306
#Sta/Elev= 30
     9.9  1996.1    19.7 1993.82    69.1 1959.32      79 1957.64    98.7 1940.58
   118.4 1935.61   167.8 1900.82   187.5 1895.87   207.3 1876.52     227 1871.77
   236.9 1860.64   266.5 1844.61   380.2 1821.23   385.2 1820.85   390.2 1821.29
   414.9 1826.25   444.6 1845.55   474.3 1854.05   503.9 1874.23   523.7 1876.04
   543.5 1892.34   592.8 1912.54   602.7 1926.03   632.3 1932.07   652.1 1952.06
   681.7 1954.93   721.2  1975.7   750.9  1973.2   770.6 1986.46   839.8 1989.23
#Mann= 3 , 0 , 0
       0      .1       0   380.2    .045       0   390.2      .1       0
Bank Sta=380.2,390.2
XS Rating Curve= 0 ,0
Exp/Cntr=0.3,0.1

Type RM Length L Ch R = 1 ,276.1   ,107.2,107.6,108.1
XS GIS Cut Line= 4
     1771417.856       85848.494     1771639.951       85727.352
     1771783.807       85517.876     1771993.283       85250.353
#Sta/Elev= 30
     9.7 1919.49    38.9 1914.14    68.1 1901.18    87.6 1884.43   136.2 1864.91
     146 1854.42   165.4  1852.2   204.3 1837.09   282.3 1822.26   404.4 1809.45
   409.4  1809.3   414.4 1809.41   458.2 1816.93   477.8 1831.91   497.3 1832.88
   517.1 1850.61   547.1 1857.04   567.1 1872.23     597 1876.19     607 1885.74
     627 1884.41     657 1897.07     677 1898.38     697 1910.74     717 1910.34
   736.9 1924.58   756.9 1922.69   786.9 1935.36   826.9 1942.67   846.9 1941.03
#Mann= 3 , 0 , 0
       0      .1       0   404.4    .045       0   414.4      .1       0
Bank Sta=404.4,414.4
XS Rating Curve= 0 ,0
Exp/Cntr=0.3,0.1

Type RM Length L Ch R = 1 ,168.5   ,135.5,137.3,139.1
XS GIS Cut Line= 4
     1771415.332       85871.208      1771725.76       85785.399
     1771906.652       85533.801     1772027.647       85270.466
#Sta/Elev= 30
    10.1 1892.49    70.5 1893.34    90.6 1887.31   120.8 1872.39   140.9 1856.97
   171.1 1844.01   221.4  1827.8   301.9 1811.51     467  1802.3     472 1802.06
     477 1802.34     502 1807.93     602 1815.25   621.9  1824.5   641.9  1824.8
   661.9  1836.1   681.9 1839.21   701.9 1850.84   721.9  1848.9   731.9 1854.58
   751.9 1856.33   771.8 1867.95   791.8 1868.23   811.8 1884.18   831.8 1886.83
   851.8 1898.51   861.8 1895.88   871.8 1900.15   881.8 1911.16   921.7  1920.2
#Mann= 3 , 0 , 0
       0      .1       0     467    .045       0     477      .1       0
Bank Sta=467,477
XS Rating Curve= 0 ,0
Exp/Cntr=0.3,0.1

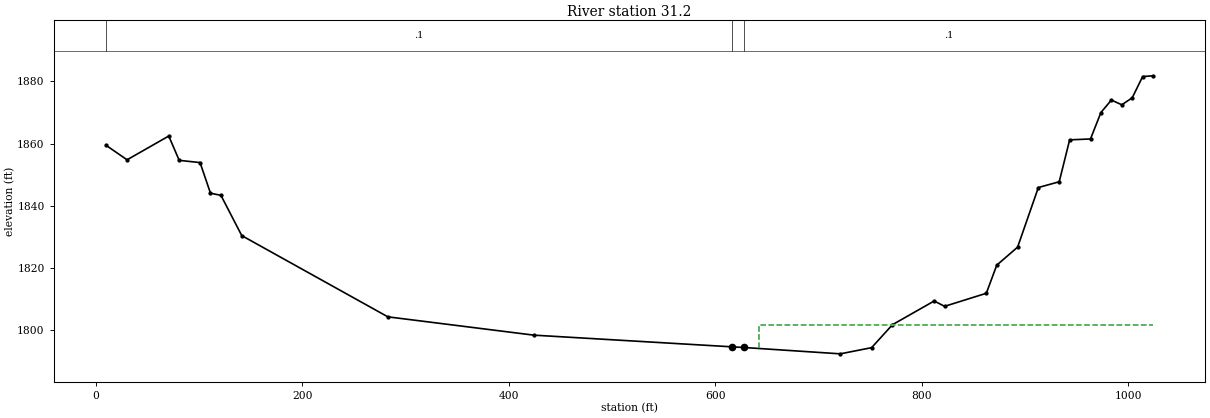
Type RM Length L Ch R = 1 ,31.2    ,41,31.2,21.3
XS GIS Cut Line= 4
     1771468.332       85904.018     1771877.188       85790.447
     1772051.302       85575.606     1772114.965       85258.775
#Sta/Elev= 30
    10.1 1859.41    30.3 1854.78    70.7 1862.43    80.8 1854.61     101 1853.89
   111.1 1844.04   121.2 1843.36   141.4  1830.4   282.9 1804.27   424.3 1798.38
  616.42 1794.62  627.75 1794.41   721.1 1792.37   751.4 1794.36   771.6 1801.74
     812 1809.37   822.1 1807.65   862.5 1811.85   872.6 1820.89   892.8 1826.69
   912.9 1845.87   933.1 1847.72   943.2  1861.2   963.4 1861.49   973.5 1869.99
   983.6    1874   993.7 1872.48  1003.8 1874.72  1013.9 1881.56    1024 1881.81
#Mann= 3 , 0 , 0
    10.1      .1       0  616.42    .045       0  627.75      .1       0
#XS Ineff= 2 , 0
                          642.17         1801.65
Permanent Ineff=
       F       F
Bank Sta=616.42,627.75
XS Rating Curve= 0 ,0
Exp/Cntr=0.3,0.1

Chan Stop Cuts=-1
Use User Specified Reach Order=0